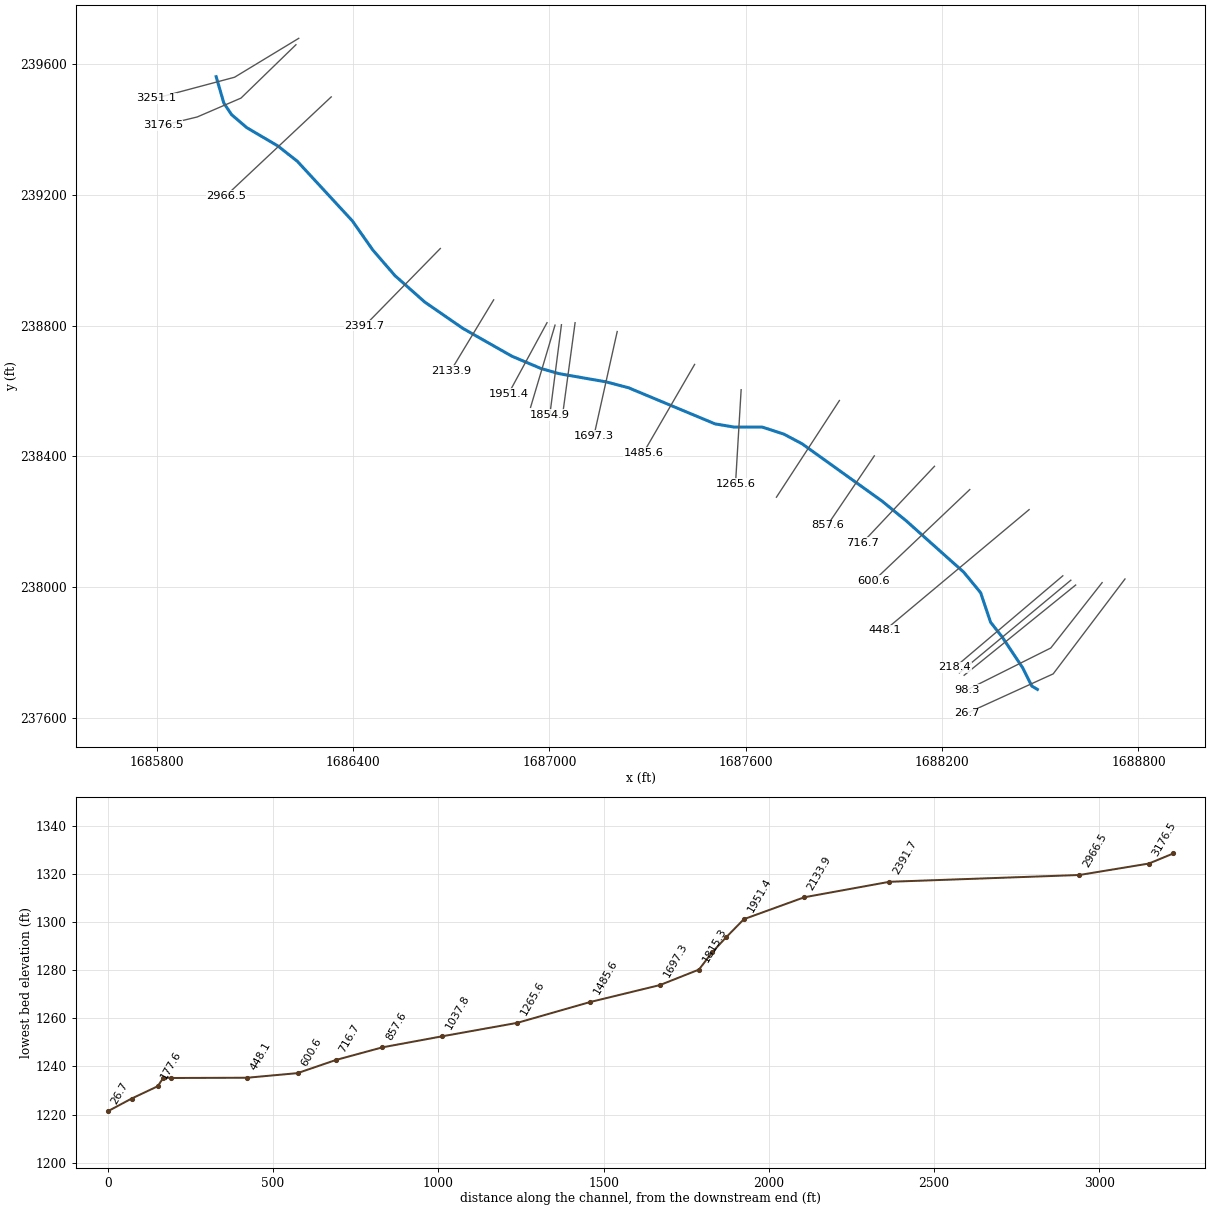
--- shrkybrnch.prj (project) ---

Proj Title=shrkybrnch
Current Plan=p01
Default Exp/Contr=0,0
English Units
Geom File=g01
Flow File=f01
Plan File=p01
BEGIN DESCRIPTION:
END DESCRIPTION:
DSS Export Rating Curves= 0
DSS Export Rating Curve Sorted= 0
DSS Export Volume Flow Curves= 0
DXF OffsetX= 0
DXF OffsetY= 0
DXF ScaleX= 0
DXF ScaleY= 0

--- shrkybrnch.p01 (plan) ---

Plan Title=Approximate Study - 100yr
Program Version=4.00
Geom File=g01
Flow File=f01
Subcritical Flow
K Sum by GR= 0
Std Step Tol= 0.01
Critical Tol= 0.01
Num of Std Step Trials= 20
Max Error Tol= 0.3
Flow Tol Ratio= 0.001
Split Flow NTrial= 30
Split Flow Tol= 0.02
Split Flow Ratio= 0.02
Log Output Level= 0
Friction Slope Method= 1
Unsteady Friction Slope Method= 2
Unsteady Bridges Friction Slope Method= 1
Parabolic Critical Depth
Global Vel Dist= 0 , 0 , 0
Global Log Level= 0
CheckData=True
Encroach Param=-1 ,0,0, 0
Run HTab= 0
Run UNet= 0
Run PostProcess= 0
Run WQNet= 0
UNET Theta= 0
UNET Theta Warmup= 0
UNET ZTol= 0
UNET ZSATol= 0
UNET MxIter= 0
UNET MaxInSteps= 0
UNET DtIC= 0
UNET DtMin= 0
UNET MaxCRTS= 0
UNET WFStab= 0
UNET SFStab= 0
UNET WFX= 1
UNET SFX= 1
UNET DSS MLevel= 1
UNET DZMax Abort= 0
UNET Convert EG Bridges= 0
UNET Use Existing IB Tables= 0
UNET Froude Reduction=False
UNET Froude Limit= 0
UNET Froude Power= 0
UNET Time Slicing=0,0, 5
Write IC File= 0
Echo Input=False
Echo Output=False
Write Detailed= 0
Detailed Automatic Start=False, 0
WQ ULTIMATE=-1
WQ Max Comp Step=1HOUR
WQ Output Interval=15MIN
WQ Output Selected Increments= 0
WQ Output face flow=0
WQ Output face velocity=0
WQ Output face area=0
WQ Output face dispersion=0
WQ Output cell volume=0
WQ Output cell surface area=0
WQ Output cell continuity=0
WQ Output face conc=0
WQ Output face dconc_dx=0
WQ Output face courant=0
WQ Output face peclet=0
WQ Output face adv mass=0
WQ Output face disp mass=0
WQ Output cell mass=0
WQ Output cell source sink temp=0
WQ Output cell source sink nsm=0
WQ Output MaxMinRange=-1
WQ Daily Max Min Mean=-1
WQ Daily Range=0
WQ Daily Time=0
WQ Create Restart=0
WQ Fixed Restart=0
WQ System Summary=False
Sorting and Armoring Iterations= 10
XS Update Threshold= 0.02
Hydraulics Update Threshold= 0.02
Energy Slope Method= 1
Volume Change Method= 0
XS Weighting Method= 0
Number of US Weighted Cross Sections= 1
Number of DS Weighted Cross Sections= 1
Upstream XS Weight=0.25
Main XS Weight=0.5
Downstream XS Weight=0.25
Number of DS XS's Weighted with US Boundary= 1
Upstream Boundary Weight= 1
Weight of XSs Associated with US Boundary= 0
Number of US XS's Weighted with DS Boundary= 1
Downstream Boundary Weight= 0.5
Weight of XSs Associated with DS Boundary= 0.5
Sediment Output Level= 4
Mass or Volume Output= 0
Output Increment Type= 1
Profile and TS Output Increment= 10
XS Output Flag= 0
XS Output Increment= 10
Disregard all LS=0
Disregard all Conn=0
Disregard all Breaches=0
Disregard all Pumps=0

--- shrkybrnch.f01 (steady flow) ---

Flow Title=USGS Regression Equation
Program Version=4.00
Number of Profiles= 1
Profile Names=P100yr
River Rch & RM=shrkybrnch,Main            ,3251.1
     366
River Rch & RM=shrkybrnch,Main            ,2391.7
     379
River Rch & RM=shrkybrnch,Main            ,218.4
     420
Boundary for River Rch & Prof#=shrkybrnch,Main            , 1
Up Type= 0
Dn Type= 3
Dn Slope=0.018657
DSS Import GetInterval= 0
DSS Import GetPeak= 0
DSS Import FillOption= 0

--- shrkybrnch.g01 (geometry) ---

Geom Title=USGS 3m DEM
Program Version=4.00

River Reach=shrkybrnch      ,Main
Reach XY= 30
     1685981.473      239560.519     1686004.891      239479.815
     1686028.448      239444.649     1686075.395      239404.476
     1686170.083      239348.843     1686229.483      239302.007
     1686397.826      239119.666     1686459.848      239031.292
       1686527.7      238952.685     1686619.211      238871.571
     1686735.774      238791.111     1686885.441      238706.151
     1686974.644      238668.527     1687029.665      238652.933
     1687173.312      238627.802     1687241.464      238609.934
     1687505.898      238499.541     1687564.039      238489.775
     1687650.142      238489.729     1687716.266       238468.22
     1687772.065       238438.64     1688016.412       238263.51
     1688090.719      238202.848     1688266.133       238046.23
     1688317.615      237983.716     1688348.259      237893.009
     1688382.908      237849.153     1688446.371      237753.871
      1688474.28      237698.029     1688491.164      237688.085

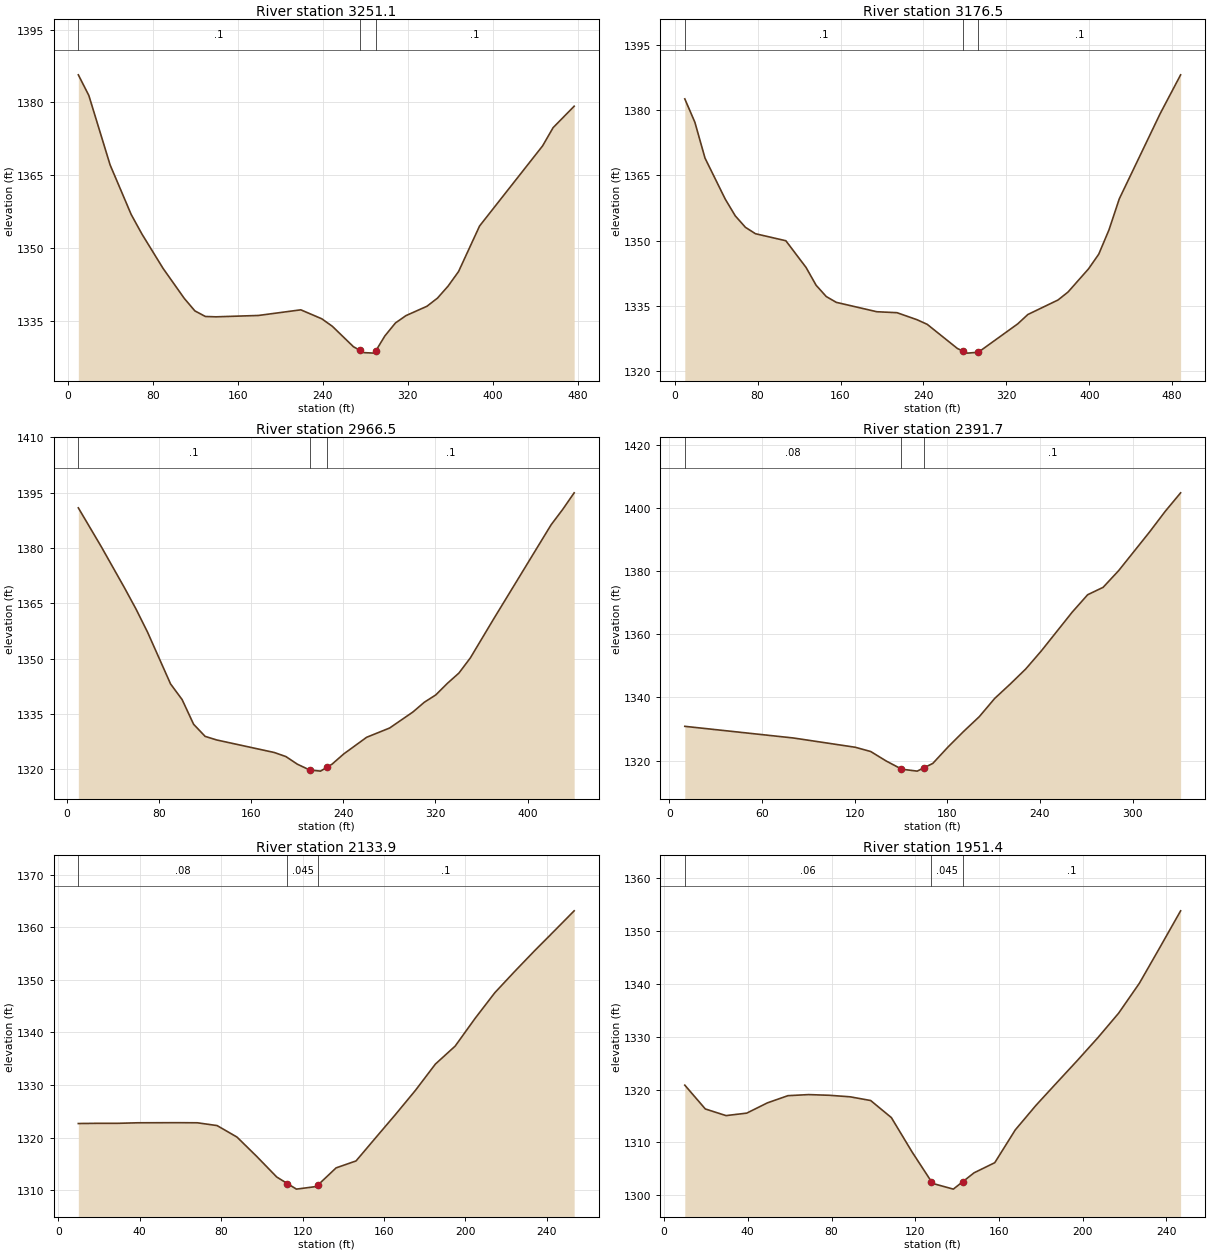
Type RM Length L Ch R = 1 ,3251.1  ,71.4,74.7,78
XS GIS Cut Line= 3
     1686233.806      239677.731     1686037.683      239558.831
     1685798.658      239495.091
#Sta/Elev= 30
      10 1385.69    19.9 1381.44    39.9 1367.16    59.8 1356.93    69.8 1352.95
    89.7 1345.88   109.7 1339.69   119.7 1337.11   129.6 1335.96   139.6 1335.89
   179.5 1336.17   219.4 1337.33   239.2 1335.48   249.1 1333.94   268.9 1329.75
   275.21328.967   278.8 1328.52   288.7 1328.42   290.2 1328.96   298.6 1331.98
   308.5 1334.63   318.4 1336.14   338.2 1338.07   348.1 1339.75     358  1342.2
   367.9 1345.21   387.7 1354.59     447 1371.07   456.9 1374.82   476.7 1379.23
#Mann= 3 , 0 , 0
      10      .1       0   275.2    .045       0   290.2      .1       0
Bank Sta=275.2,290.2
XS Rating Curve= 0 ,0
Exp/Cntr=0.3,0.1

Type RM Length L Ch R = 1 ,3176.5  ,202.3,210,217.7
XS GIS Cut Line= 4
     1686225.226      239658.118     1686057.295      239495.091
     1685923.686      239437.479      1685818.27      239411.738
#Sta/Elev= 30
     9.8 1382.55    19.5  1377.2    29.3 1368.96    48.8 1359.55    58.5  1355.7
    68.3 1353.07      78  1351.6   107.3 1349.99   126.8 1343.85   136.5 1339.77
   146.3 1337.18     156 1335.85     195  1333.7   214.5 1333.48     234 1331.85
   243.7  1330.8   272.8 1325.26     2781324.692   282.5  1324.2     2931324.407
     331 1330.92   340.7 1333.06   369.8 1336.39   379.5 1338.22   399.3 1343.55
   409.1  1346.9     419 1352.49   428.9 1359.59   468.3 1379.13   488.1 1388.07
#Mann= 3 , 0 , 0
     9.8      .1       0     278    .045       0     293      .1       0
Bank Sta=278,293
XS Rating Curve= 0 ,0
Exp/Cntr=0.3,0.1

Type RM Length L Ch R = 1 ,2966.5  ,573.8,574.8,575.8
XS GIS Cut Line= 2
     1686333.093      239498.768     1686011.942      239197.229
#Sta/Elev= 30
      10  1390.9      30 1380.32    50.1 1369.19    60.1 1363.43    70.1 1357.17
    90.1 1343.11   100.1 1338.88   110.1 1332.17   120.1 1328.89   130.2 1327.91
   180.2 1324.51   190.2 1323.41   200.2 1321.34   210.81319.774   220.3 1319.46
   225.81320.501   230.3 1321.35   240.3 1324.09   260.3 1328.64   280.3 1331.16
   300.4 1335.48   310.4 1338.15   320.4 1340.15   330.4 1343.27   340.4 1346.05
   350.4  1350.2   370.4 1360.65   420.5 1386.31   430.5 1390.46   440.5 1394.98
#Mann= 3 , 0 , 0
      10      .1       0   210.8    .045       0   225.8      .1       0
Bank Sta=210.8,225.8
XS Rating Curve= 0 ,0
Exp/Cntr=0.3,0.1

Type RM Length L Ch R = 1 ,2391.7  ,252.6,257.8,263
XS GIS Cut Line= 2
     1686666.503      239035.427     1686434.832      238798.853
#Sta/Elev= 24
      10 1330.83    80.3 1327.14   120.4  1324.2   130.4 1322.85   140.5 1319.83
     1501317.379   150.5 1317.25   160.5 1316.64     1651317.726   170.6 1319.08
   180.6 1324.35   190.6 1329.23   200.7 1333.88   210.7 1339.67   220.7  1344.2
   230.8    1349   240.8 1354.67   260.9 1367.01   270.9 1372.52   280.9 1374.86
     291 1380.17     311 1392.41   321.1 1398.92   331.1  1404.8
#Mann= 3 , 0 , 0
      10     .08       0     150    .045       0     165      .1       0
Bank Sta=150,165
XS Rating Curve= 0 ,0
Exp/Cntr=0.3,0.1

Type RM Length L Ch R = 1 ,2133.9  ,181.5,182.5,183.6
XS GIS Cut Line= 2
      1686829.53      238878.528     1686698.373      238661.567
#Sta/Elev= 30
     9.8 1322.68    19.5 1322.72    29.3 1322.72      39 1322.82    48.8 1322.83
    58.5 1322.84    68.3 1322.82      78 1322.29    87.8  1320.1    97.5 1316.42
   107.3 1312.52   109.5 1311.99   112.51311.278     117 1310.21   124.5 1310.59
   126.8 1310.71   127.51310.965   136.5 1314.25   146.3 1315.57     156    1320
   165.8 1324.45   175.5 1328.99   185.3 1333.98     195 1337.39   204.8 1342.66
   214.5 1347.54   224.3  1351.6     234  1355.5   243.8 1359.31   253.5 1363.11
#Mann= 3 , 0 , 0
     9.8     .08       0   112.5    .045       0   127.5      .1       0
Bank Sta=112.5,127.5
XS Rating Curve= 0 ,0
Exp/Cntr=0.3,0.1

Type RM Length L Ch R = 1 ,1951.4  ,49.7,54.3,59
XS GIS Cut Line= 2
     1686992.558      238808.659     1686874.884      238591.698
#Sta/Elev= 29
     9.9 1320.83    19.7 1316.32    29.6 1315.06    39.5 1315.53    49.4 1317.48
    59.2 1318.84    69.1 1319.04      79 1318.91    88.9 1318.62    98.7 1317.92
   108.6 1314.68   118.5 1308.17   127.71302.575   128.3 1302.21   130.7 1301.95
   138.2 1301.13   142.71302.534   145.7 1303.47   148.1 1304.22     158 1306.14
   167.8 1312.35   177.7 1317.01   187.6 1321.28   197.5 1325.52   207.3 1329.84
   217.2 1334.48   227.1 1340.14   236.9 1346.93   246.8 1353.86
#Mann= 3 , 0 , 0
     9.9     .06       0   127.7    .045       0   142.7      .1       0
Bank Sta=127.7,142.7
XS Rating Curve= 0 ,0
Exp/Cntr=0.3,0.1

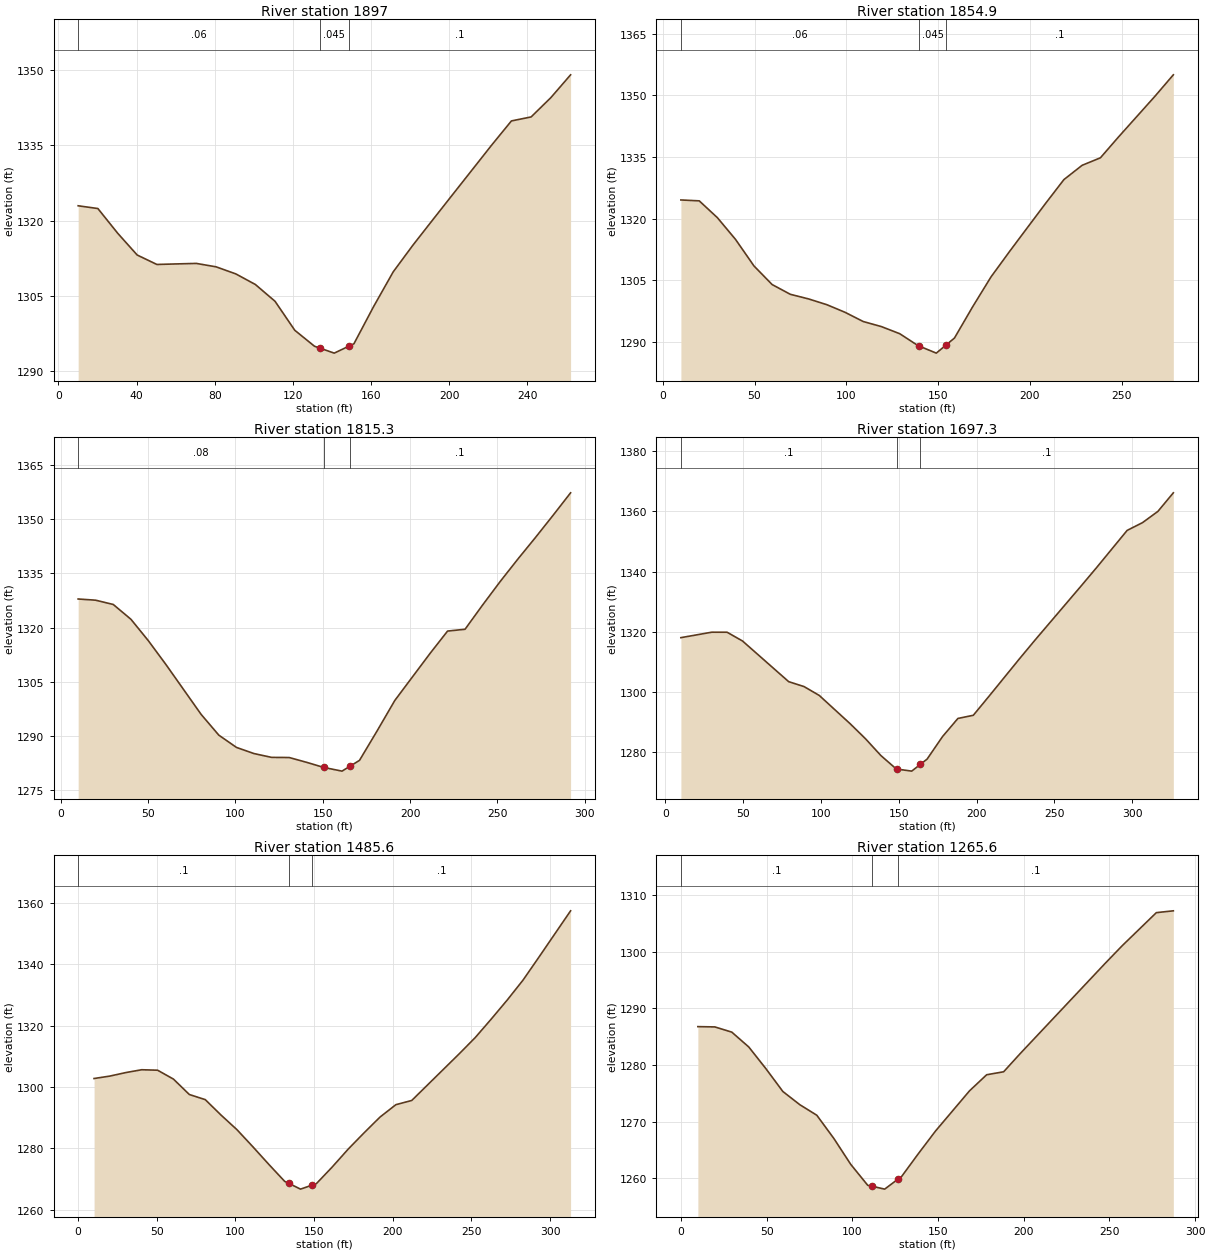
Type RM Length L Ch R = 1 ,1897    ,38.5,42.2,45.8
XS GIS Cut Line= 2
     1687017.073      238801.305     1686942.301      238550.022
#Sta/Elev= 28
    10.1 1322.94    20.2 1322.39    30.3 1317.48    40.3 1313.12    50.4 1311.23
    60.5 1311.34    70.6 1311.44    80.7 1310.76    90.8 1309.35   100.8 1307.24
   110.9 1303.88     121  1298.1   131.1 1294.91   133.7 1294.56   141.2 1293.54
   148.7 1294.93   151.3 1295.42   161.3 1302.79   171.4 1309.76   181.5 1315.09
   191.6 1320.12   201.7 1325.12   211.8 1330.11   221.8 1335.05   231.9 1339.87
     242 1340.67   252.1 1344.52   262.2 1349.07
#Mann= 3 , 0 , 0
    10.1     .06       0   133.7    .045       0   148.7      .1       0
Bank Sta=133.7,148.7
XS Rating Curve= 0 ,0
Exp/Cntr=0.3,0.1

Type RM Length L Ch R = 1 ,1854.9  ,39.7,39.6,39.4
XS GIS Cut Line= 2
     1687036.685      238802.531     1687001.138      238526.732
#Sta/Elev= 29
     9.9 1324.56    19.9 1324.34    29.8 1320.24    39.7 1314.94    49.7 1308.51
    59.6 1303.98    69.5 1301.61    79.5 1300.48    89.4 1299.08    99.3 1297.23
   109.2 1294.99   119.2 1293.74   129.1 1292.02     139 1289.14   139.51289.048
     149  1287.3   154.51289.339   158.9 1290.97   168.8 1298.57   178.8 1305.84
   188.7  1311.9   198.6 1317.82   208.6 1323.76   218.5 1329.51   228.4 1332.98
   238.4 1334.82   248.3 1339.91   268.1 1349.79   278.1    1355
#Mann= 3 , 0 , 0
     9.9     .06       0   139.5    .045       0   154.5      .1       0
Bank Sta=139.5,154.5
XS Rating Curve= 0 ,0
Exp/Cntr=0.3,0.1

Type RM Length L Ch R = 1 ,1815.3  ,119.9,118,116.1
XS GIS Cut Line= 2
     1687078.362      238808.659     1687039.137      238519.378
#Sta/Elev= 28
    10.1 1327.91    20.1 1327.58    30.2 1326.39    40.3 1322.29    50.3 1316.33
    60.4  1309.7    80.5 1295.91    90.6 1290.17   100.7 1286.77   110.7 1285.07
   120.8 1284.01   130.9 1283.97   140.9 1282.63   150.61281.228   161.1  1280.2
   165.61281.544   171.1 1283.18   181.2 1291.37   191.3 1299.78   211.4 1312.78
   221.5 1319.02   231.5 1319.52   241.6 1326.28   251.7 1332.81   261.7 1338.96
   271.8 1344.96   281.9 1351.12   291.9 1357.34
#Mann= 3 , 0 , 0
    10.1     .08       0   150.6    .045       0   165.6      .1       0
Bank Sta=150.6,165.6
XS Rating Curve= 0 ,0
Exp/Cntr=0.3,0.1

Type RM Length L Ch R = 1 ,1697.3  ,218.6,211.8,204.9
XS GIS Cut Line= 2
     1687207.067      238781.693     1687135.973      238462.992
#Sta/Elev= 27
     9.9 1318.07    29.7 1319.88    39.6 1319.87    49.5 1316.97    79.2 1303.47
    89.1 1301.83    98.9 1298.88   118.7 1289.52   128.6 1284.52   138.5 1278.94
   148.4 1274.49   148.81274.462   158.3 1273.78   163.81275.995   168.2 1277.77
   178.1 1285.23     188 1291.26   197.9 1292.31   207.8  1298.5   227.6 1311.07
   237.5 1317.22   267.2 1335.21   277.1 1341.28   296.8 1353.66   306.7 1356.24
   316.6 1359.98   326.5 1366.13
#Mann= 3 , 0 , 0
     9.9      .1       0   148.8    .045       0   163.8      .1       0
Bank Sta=148.8,163.8
XS Rating Curve= 0 ,0
Exp/Cntr=0.3,0.1

Type RM Length L Ch R = 1 ,1485.6  ,209.5,219.9,230.4
XS GIS Cut Line= 2
     1687443.641      238681.179     1687286.743      238410.284
#Sta/Elev= 30
    10.1 1302.75    20.2 1303.55    30.3 1304.69    40.4 1305.61    50.5 1305.46
    60.6 1302.56    70.7 1297.54    80.8 1295.88    90.9 1290.82     101 1286.07
   111.1 1280.51   121.2  1274.8   131.3 1269.25   133.9  1268.6   141.4 1266.72
   148.9 1268.05   151.5 1268.52   161.6 1273.96   171.7 1279.76   181.8 1285.06
   191.9 1290.18     202 1294.23   212.1  1295.6   242.4 1310.86   252.5 1316.11
   262.6 1322.09   272.7 1328.25   282.8 1334.77   292.9 1342.24   313.1 1357.38
#Mann= 3 , 0 , 0
       0      .1       0   133.9    .045       0   148.9      .1       0
Bank Sta=133.9,148.9
XS Rating Curve= 0 ,0
Exp/Cntr=0.3,0.1

Type RM Length L Ch R = 1 ,1265.6  ,239.5,227.8,216.2
XS GIS Cut Line= 2
     1687585.831      238603.956      1687568.67      238317.125
#Sta/Elev= 25
     9.9 1286.78    19.8 1286.73    29.7 1285.81    39.6 1283.19    49.5  1279.4
    59.5 1275.33    69.4    1273    79.3 1271.14    89.2 1267.06    99.1 1262.47
     109 1258.78   111.4 1258.62   118.9  1258.1   126.4  1259.8   128.8 1260.34
   138.7 1264.42   148.6 1268.37   168.4 1275.45   178.4 1278.29   188.3 1278.81
   198.2  1282.1   247.7    1298   257.6  1301.1   277.4  1306.9   287.3 1307.22
#Mann= 3 , 0 , 0
       0      .1       0   111.4    .045       0   126.4      .1       0
Bank Sta=111.4,126.4
XS Rating Curve= 0 ,0
Exp/Cntr=0.3,0.1

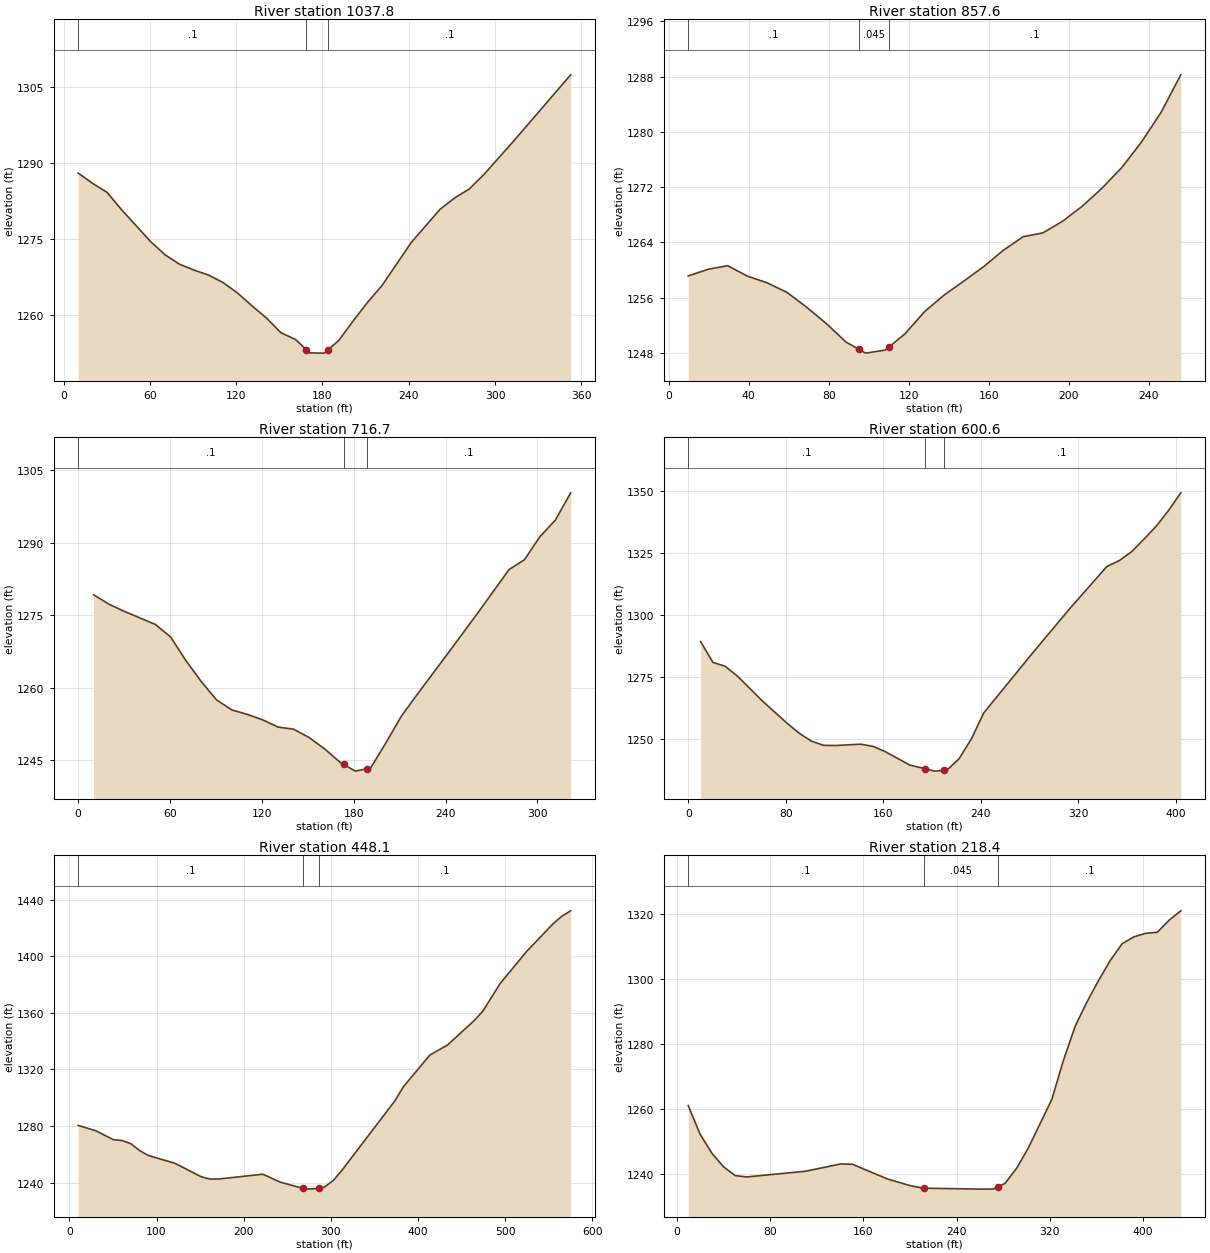
Type RM Length L Ch R = 1 ,1037.8  ,180.6,180.2,179.8
XS GIS Cut Line= 2
     1687886.144       238570.86     1687693.698      238275.449
#Sta/Elev= 30
    10.1 1287.96    20.1 1285.94    30.2 1284.16    40.3 1280.74    60.4 1274.49
    70.5 1271.87    80.6 1270.01    90.7 1268.85   100.7 1267.88   110.8 1266.42
   120.9 1264.35     131 1261.81     141 1259.43   151.1 1256.52   161.2  1255.2
   168.81253.186   171.2 1252.55   181.3  1252.5   183.81253.123   191.4 1255.02
   201.5  1258.9   211.5 1262.55   221.6 1265.89   241.8 1274.32   261.9 1280.86
     272 1283.08   282.1 1284.83   292.1 1287.63   312.3 1294.06   352.6 1307.31
#Mann= 3 , 0 , 0
    10.1      .1       0   168.8    .045       0   183.8      .1       0
Bank Sta=168.8,183.8
XS Rating Curve= 0 ,0
Exp/Cntr=0.3,0.1

Type RM Length L Ch R = 1 ,857.6   ,144.5,140.9,137.2
XS GIS Cut Line= 2
     1687992.786      238401.704     1687849.371      238189.645
#Sta/Elev= 30
     9.8 1259.13    19.7 1260.09    29.5 1260.61    39.4 1259.09    49.2 1258.13
    59.1 1256.75    68.9 1254.61    78.8 1252.23    88.6 1249.55      91 1249.16
      951248.509    98.5 1247.94     106 1248.28   108.3 1248.39     1101248.797
   118.2 1250.76     128 1253.98   137.8 1256.38   147.7 1258.41   157.5 1260.48
   167.4 1262.87   177.2 1264.81   187.1 1265.37   196.9 1267.05   206.8 1269.24
   216.6 1271.84   226.5 1274.83   236.3 1278.51   246.2 1282.86     256 1288.27
#Mann= 3 , 0 , 0
     9.8      .1       0      95    .045       0     110      .1       0
Bank Sta=95,110
XS Rating Curve= 0 ,0
Exp/Cntr=0.3,0.1

Type RM Length L Ch R = 1 ,716.7   ,117.4,116.1,114.9
XS GIS Cut Line= 2
     1688176.652      238369.834     1687956.013      238135.712
#Sta/Elev= 30
    10.1 1279.23    20.1 1277.28    30.2 1275.78    50.3 1273.11    60.3 1270.51
    70.4 1265.59    80.4 1261.24    90.5 1257.42   100.5 1255.36   110.6 1254.43
   120.6  1253.3   130.7 1251.81   140.7 1251.38   150.8 1249.66   160.9 1247.32
   170.9 1244.56   173.5 1244.08     181 1242.69   188.5 1243.16     191 1243.32
   201.1  1248.6   211.1 1254.07   221.2 1258.47   241.3 1266.99   261.4 1275.62
   281.5 1284.47   291.5 1286.49   301.6 1291.26   311.7 1294.69   321.7 1300.35
#Mann= 3 , 0 , 0
       0      .1       0   173.5    .045       0   188.5      .1       0
Bank Sta=173.5,188.5
XS Rating Curve= 0 ,0
Exp/Cntr=0.3,0.1

Type RM Length L Ch R = 1 ,600.6   ,153.9,152.4,151
XS GIS Cut Line= 2
     1688284.519      238298.739     1687991.561      238020.489
#Sta/Elev= 30
    10.1 1289.35    20.2 1280.99    30.3 1279.41    40.4 1275.42    60.6 1265.55
    80.8 1256.59    90.9 1252.51     101  1249.3   111.1 1247.59   121.2 1247.54
   141.4 1248.07   151.5  1247.2   161.6 1245.07   181.8 1239.64   194.5 1238.19
     202 1237.23   209.5 1237.49   212.1 1237.58   222.2 1242.25   232.3 1250.28
   242.4 1260.67   282.8 1284.97   313.1 1302.71   343.4 1319.59   353.5 1321.92
   363.6 1325.49   373.7 1330.49   383.8 1335.75   393.9 1342.05     404  1349.2
#Mann= 3 , 0 , 0
       0      .1       0   194.5    .045       0   209.5      .1       0
Bank Sta=194.5,209.5
XS Rating Curve= 0 ,0
Exp/Cntr=0.3,0.1

Type RM Length L Ch R = 1 ,448.1   ,229.6,229.8,229.9
XS GIS Cut Line= 2
     1688465.933      238237.451     1688024.656      237868.494
#Sta/Elev= 30
    10.1 1280.41    30.3 1276.62    50.5 1270.31    60.5 1269.69    70.6 1267.45
    80.7 1262.57    90.8 1259.08   121.1 1253.59   151.4 1244.05   161.5 1242.42
   171.6 1242.49     222 1245.87   242.2 1240.22     2681235.884   272.5 1235.32
     2861235.816   292.6 1236.72   302.7  1241.4   312.8 1248.67   373.4 1297.68
   383.5 1307.94   413.7  1330.2   433.9 1337.27   464.2  1354.4   474.3 1361.11
   494.5 1380.97   524.7 1403.48     555 1423.04   565.1 1428.42   575.2  1432.2
#Mann= 3 , 0 , 0
    10.1      .1       0     268    .045       0     286      .1       0
Bank Sta=268,286
XS Rating Curve= 0 ,0
Exp/Cntr=0.3,0.1

Type RM Length L Ch R = 1 ,218.4   ,23.7,23.5,23.3
XS GIS Cut Line= 2
     1688568.898      238035.199     1688239.166      237755.723
#Sta/Elev= 30
    10.1 1260.95    20.1 1252.22    30.2 1246.36    40.2 1242.13    50.3 1239.39
    60.3 1238.98   110.6 1240.73   140.7 1242.98   150.8 1242.88   180.9 1238.34
     201 1236.22   211.91235.506   261.4 1235.22   271.4 1235.26   275.91236.022
   281.5 1236.97   291.5 1241.64   301.6 1247.94   321.7 1262.88   331.7 1274.98
   341.8  1285.5   351.8 1292.88   361.9  1299.6   371.9 1305.72     382 1310.85
     392 1312.93   402.1 1314.02   412.1 1314.34   422.2 1318.06   432.2 1320.95
#Mann= 3 , 0 , 0
    10.1      .1       0   211.9    .045       0   275.9      .1       0
Bank Sta=211.9,275.9
XS Rating Curve= 0 ,0
Exp/Cntr=0.3,0.1

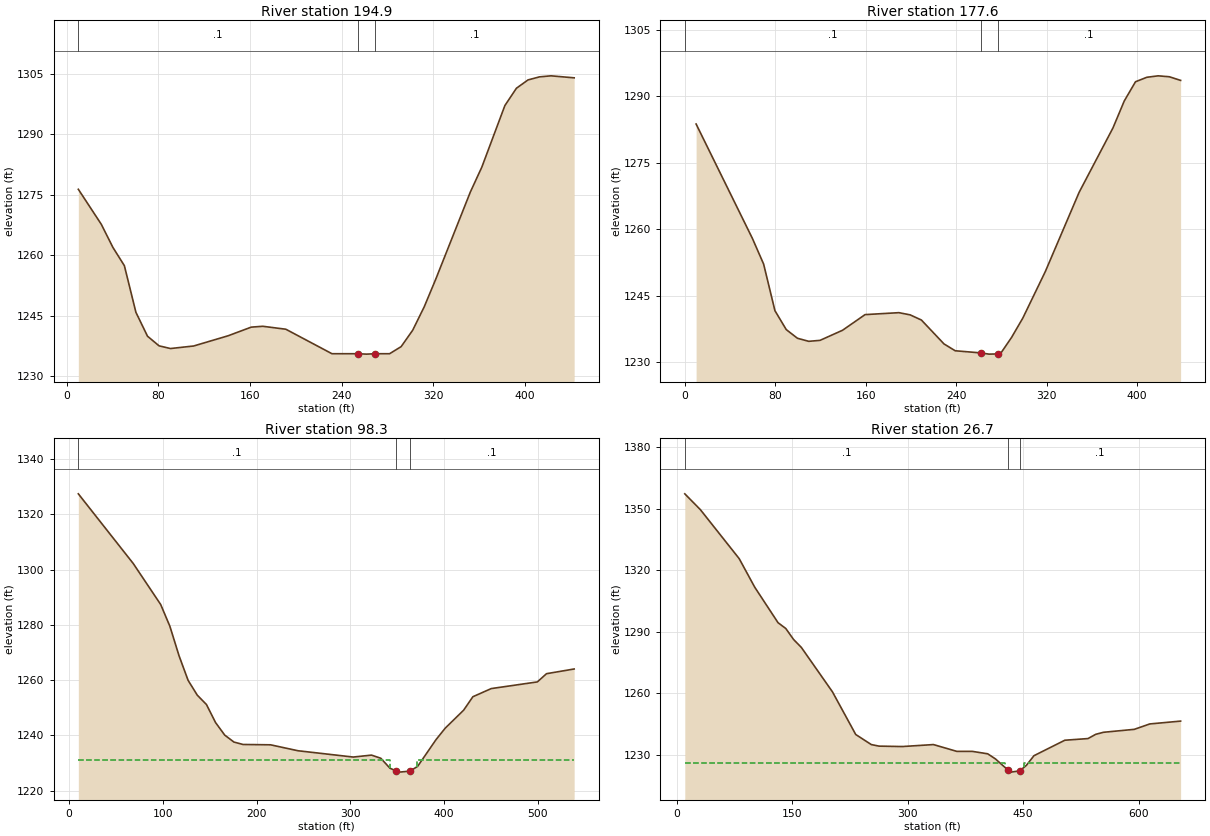
Type RM Length L Ch R = 1 ,194.9   ,17.5,17.3,17
XS GIS Cut Line= 2
     1688593.413      238021.715     1688252.649      237738.562
#Sta/Elev= 30
    10.1 1276.37    30.2 1267.65    40.3 1261.92    50.3 1257.39    60.4 1245.78
    70.5 1239.86    80.6 1237.46    90.6 1236.79   110.8 1237.42     141 1239.97
   161.1 1242.11   171.2 1242.32   191.3 1241.59   231.6  1235.5   254.3  1235.5
   261.8  1235.4   269.3  1235.5   281.9  1235.5     292 1237.26   302.1 1241.34
   312.2 1247.18   322.2    1254   352.4 1275.66   362.5  1281.9   382.6 1297.18
   392.7 1301.49   402.8 1303.55   412.8 1304.31   422.9 1304.57   443.1 1304.07
#Mann= 3 , 0 , 0
    10.1      .1       0   254.3    .045       0   269.3      .1       0
Bank Sta=254.3,269.3
XS Rating Curve= 0 ,0
Exp/Cntr=0.3,0.1

Type RM Length L Ch R = 1 ,177.6   ,84.3,79.3,74.4
XS GIS Cut Line= 2
     1688608.123      238007.006     1688267.359      237731.207
#Sta/Elev= 30
      10 1283.75    59.8 1257.91    69.7 1252.13    79.7 1241.61    89.7 1237.34
    99.6 1235.38   109.6 1234.69   119.6 1234.91   139.5 1237.19   159.4 1240.72
   189.3 1241.16   199.3 1240.66   209.2  1239.5   229.2  1234.1   239.1 1232.56
   261.5 1232.08     269  1231.8   276.5 1231.84     279 1231.86   288.9 1235.56
   298.9 1239.95   318.8 1250.46   348.7 1268.35   378.6 1282.88   388.6 1288.97
   398.5 1293.29   408.5  1294.3   418.5 1294.63   428.4 1294.42   438.4  1293.6
#Mann= 3 , 0 , 0
       0      .1       0   261.5    .045       0   276.5      .1       0
Bank Sta=261.5,276.5
XS Rating Curve= 0 ,0
Exp/Cntr=0.3,0.1

Type RM Length L Ch R = 1 ,98.3    ,72.4,71.6,70.8
XS GIS Cut Line= 3
     1688689.024       238014.36     1688532.125       237814.56
     1688277.165       237687.08
#Sta/Elev= 30
     9.8 1327.42    68.4  1302.2    97.7 1287.36   107.5 1279.51   117.3  1268.8
     127 1259.88   136.8 1254.52   146.6 1251.13   156.3  1244.6   166.1 1240.06
   175.9 1237.55   185.6 1236.67     215 1236.55   244.3  1234.4   303.2 1232.12
   322.8 1232.82   332.7 1231.68   342.5 1228.06   348.81227.159   352.3 1226.66
   363.81227.016     372 1228.74   391.7 1238.45   401.5 1242.59   421.1 1249.08
     431 1253.96   450.6 1256.91   499.8 1259.32   509.6  1262.3   539.1    1264
#Mann= 3 , 0 , 0
     9.8      .1       0   348.8    .045       0   363.8      .1       0
#XS Ineff= 2 , 0
       0     342    1231     371       0    1231
Permanent Ineff=
       F       F
Bank Sta=348.8,363.8
XS Rating Curve= 0 ,0
Exp/Cntr=0.3,0.1

Type RM Length L Ch R = 1 ,26.7    ,10.2,26.7,43.2
XS GIS Cut Line= 3
     1688758.882      238025.498      1688539.48      237735.498
     1688274.713      237614.759
#Sta/Elev= 30
    10.1 1357.17    30.3 1349.47    80.8 1325.56     101 1311.63   131.3 1294.31
   141.4 1291.46   151.5 1286.12   161.6 1282.25     202  1260.6   232.3 1239.77
   252.5 1234.87   262.6  1234.1   292.9  1233.9   333.3 1234.86   363.6 1231.55
   383.7 1231.55   403.8 1230.36   413.8 1227.89   430.41222.358   433.9 1221.42
   445.41222.032     454 1224.68     464 1229.44   504.1 1236.98   534.2 1237.79
   544.3 1239.87   554.3 1240.85   594.4 1242.29   614.5 1244.92   654.6 1246.31
#Mann= 3 , 0 , 0
    10.1      .1       0   430.4    .045       0   445.4      .1       0
#XS Ineff= 2 , 0
       0     426    1226     451       0    1226
Permanent Ineff=
       F       F
Bank Sta=430.4,445.4
XS Rating Curve= 0 ,0
Exp/Cntr=0.3,0.1

Chan Stop Cuts=-1
Use User Specified Reach Order=0